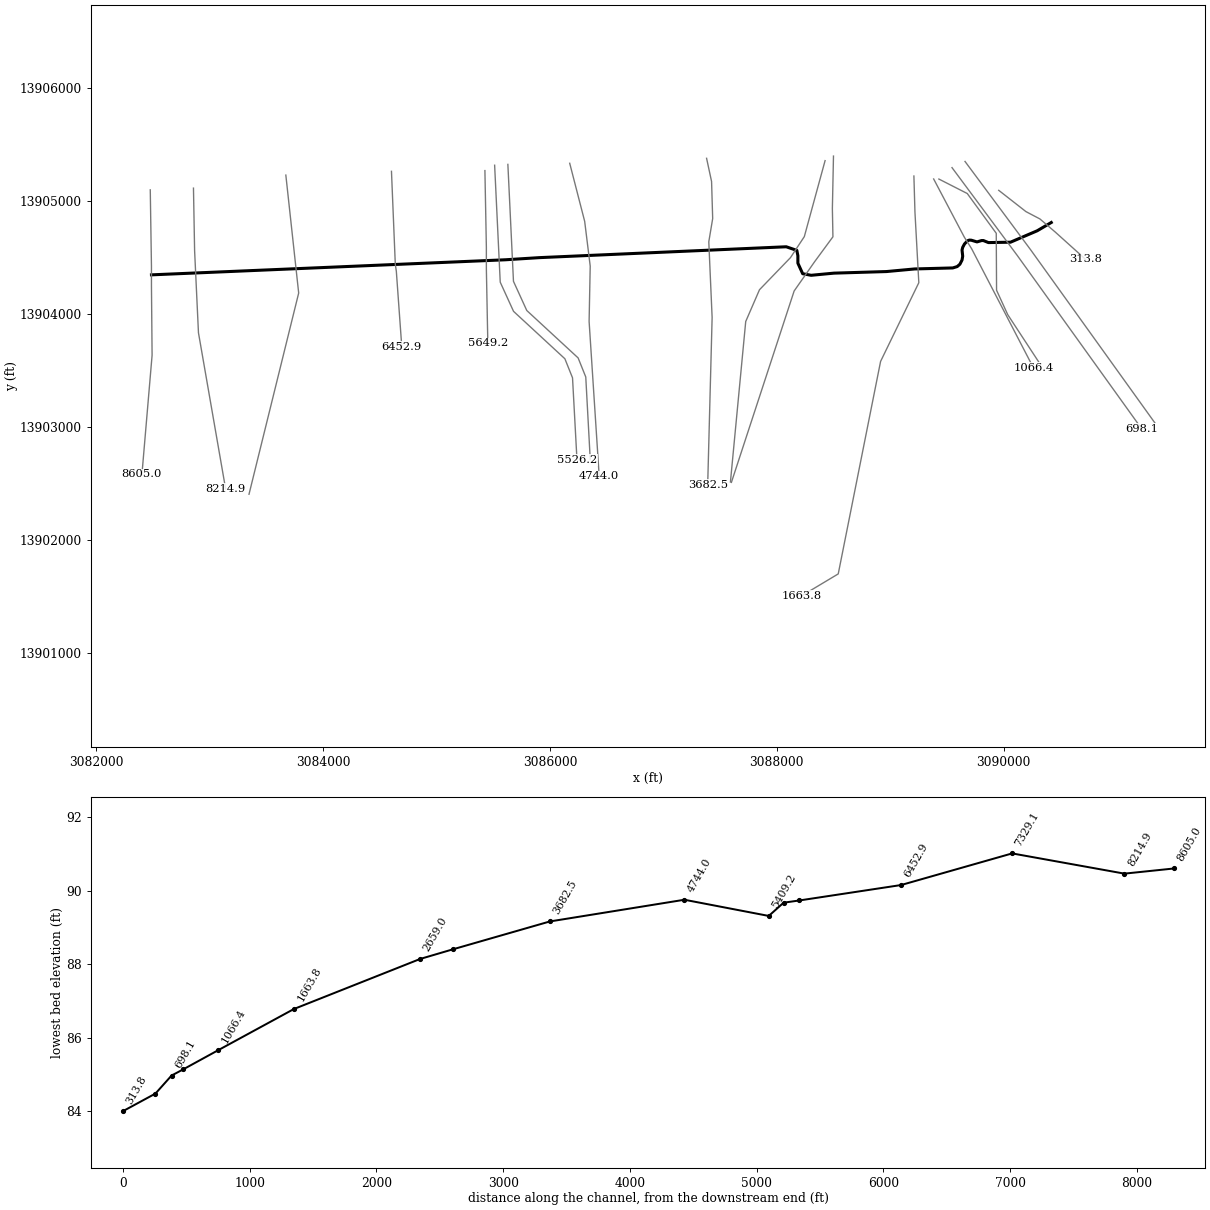
--- P148-00-00.PRJ (project) ---

Proj Title=P148-00-00
Current Plan=p02
Default Exp/Contr=.3,.1
English Units
Geom File=g01
Flow File=f01
Flow File=f02
Plan File=p01
Plan File=p02
Y Axis Title=Elevation
X Axis Title(PF)=Main Channel Distance
X Axis Title(XS)=Station
BEGIN DESCRIPTION:
Greens Bayou Watershed
Tributary 34.60 to Greens Bayou
HCFCD Unit P148-00-00
Flood Hazard Model
10, 2, 1, 0.2% Event
Filename P148-00-00.prj
Prepared by:  Watershed Concepts  Date:
Reviewed by:                      Date:
STATUS FINAL
END DESCRIPTION:
DSS Export Rating Curves= 0
DSS Export Rating Curve Sorted= 0
DSS Export Volume Flow Curves= 0
DXF OffsetX= 0
DXF OffsetY= 0
DXF ScaleX= 1
DXF ScaleY= 10

--- P148-00-00.p02 (plan) ---

Plan Title=Floodway
Version=Version 3.0.1  Mar 2001
Short Identifier=Floodway0607
Geom File=g01
Flow File=f02
Subcritical Flow
K Sum by GR= 0
Std Step Tol= 0.01
Critical Tol= 0.01
Num of Std Step Trials= 20
Max Error Tol= 0.3
Flow Tol Ratio= 0.001
Split Flow NTrial= 30
Split Flow Tol= 0.02
Split Flow Ratio= 0.02
Log Output Level= 0
Friction Slope Method= 1
Unsteady Friction Slope Method= 2
Parabolic Critical Depth
Global Vel Dist= 0 , 0 , 0
Global Log Level= 0
CheckData=True
Encroach Param=-1 ,0,0, 2
Encroach River=P148-00-00
Encroach Reach=Reach - 1
Encroach Node=8605.0
       1    4955    5038
Encroach Node=8214.9
       1    4965    5100
Encroach Node=7329.1
       1    4960    5105
Encroach Node=6452.9
       1    4962    5190
Encroach Node=5649.2
       1    4945    5225
Encroach Node=5526.2
       1    4918    5295
Encroach Node=5467.7
       1    4918    5295
Encroach Node=5409.2
       1    4918    5295
Encroach Node=4744.0
       1    4948    5220
Encroach Node=3682.5
       1  4942.5    5150
Encroach Node=2915.2
       1  4949.2    5207
Encroach Node=2659.0
       1    4934    5200
Encroach Node=1663.8
       1  4969.4    5490
Encroach Node=1066.4
       1    4960    5047
Encroach Node=791.0
       1 4954.33 5048.89
Encroach Node=698.1
       1 4954.33 5048.89
Encroach Node=634.6
       1 4954.33 5048.89
Encroach Node=571.1
       1 4954.33 5048.89
Encroach Node=313.8
       1  4947.5  5064.2
Encroach Reach=P148-00-00_0003
Encroach Node=8605.0
       1    4955    5038
Encroach Node=8214.9
       1    4965    5100
Encroach Node=7329.1
       1    4960    5105
Encroach Node=6452.9
       1    4962    5190
Encroach Node=5649.2
       1    4945    5225
Encroach Node=5526.2
       1    4918    5295
Encroach Node=5467.7
       1    4918    5295
Encroach Node=5409.2
       1    4918    5295
Encroach Node=4744.0
       1    4948    5220
Encroach Node=3682.5
       1  4942.5    5150
Encroach Node=2915.2
       1  4949.2    5207
Encroach Node=2659.0
       1    4934    5200
Encroach Node=1663.8
       1  4969.4    5490
Encroach Node=1066.4
       1    4960    5047
Encroach Node=791.0
       1 4954.33 5048.89
Encroach Node=698.1
       1 4954.33 5048.89
Encroach Node=634.6
       1 4954.33 5048.89
Encroach Node=571.1
       1 4954.33 5048.89
Encroach Node=313.8
       1  4947.5  5064.2
Computation Interval=1HOUR
Output Interval=1HOUR
Run HTab= 0
Run UNet= 0
Run PostProcess= 0
UNET Theta= 1
UNET ZTol= 0.02
UNET ZSATol= 0.1
UNET MxIter= 20
UNET MaxInSteps= 20
UNET DtIC= 0
UNET DtMin= 0
UNET MaxCRTS= 20
UNET WFStab= 2
UNET SFStab= 1
UNET WFX= 1
UNET SFX= 1
UNET Convert EG Bridges=-1
UNET Use Existing IB Tables=-1
Instantaneous Interval=1HOUR
Write IC File= 0
Write Velocity= 0
Write Detailed= 0

--- P148-00-00.p01 (plan) ---

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Plan Title=FEMA Effective June 2007
Short Identifier=FEMAeff0607
Geom File= g01
Flow File= f01
Interactive Comp Mode
Encroach Param= -1, 0, 0, 0

--- P148-00-00.f02 (steady flow) ---

Flow Title= Floodway
Number of Profiles= 2
Profile Names=1PCT_100yr, 1PCTFloodway_100yrFW
River Rch & RM=P148-00-00,P148-00-00_0003,8605.0
    1530    1530
River Rch & RM=P148-00-00,P148-00-00_0003,8214.9
    1575    1575
River Rch & RM=P148-00-00,P148-00-00_0003,7329.1
    1620    1620
River Rch & RM=P148-00-00,P148-00-00_0003,6452.9
    1663    1663
River Rch & RM=P148-00-00,P148-00-00_0003,5649.2
    1669    1669
River Rch & RM=P148-00-00,P148-00-00_0003,5526.2
    1701    1701
River Rch & RM=P148-00-00,P148-00-00_0003,4744
    1745    1745
River Rch & RM=P148-00-00,P148-00-00_0003,3682.5
    1788    1788
River Rch & RM=P148-00-00,P148-00-00_0003,2659
    1831    1831
River Rch & RM=P148-00-00,P148-00-00_0003,1663.8
    1874    1874
River Rch & RM=P148-00-00,P148-00-00_0003,698.1
    2141    2141
Boundary for River Rch & Prof#=P148-00-00,P148-00-00_0003, 1
Up Type= 0
Dn Type= 3
Dn Slope= 0.00170
Boundary for River Rch & Prof#=P148-00-00,P148-00-00_0003, 2
Up Type= 0
Dn Type= 1
Dn Known WS=93.05

--- P148-00-00.f01 (steady flow) ---

Flow Title= FEMA Effective June 2007
Number of Profiles= 4
Profile Names=10PCT_10yr, 2PCT_50yr, 1PCT_100yr, 0.2PCT_500yr
River Rch & RM=P148-00-00,P148-00-00_0003,8605.0
     658    1211    1530    2473
River Rch & RM=P148-00-00,P148-00-00_0003,8214.9
     684    1249    1575    2536
River Rch & RM=P148-00-00,P148-00-00_0003,7329.1
     710    1288    1620    2600
River Rch & RM=P148-00-00,P148-00-00_0003,6452.9
     736    1325    1663    2659
River Rch & RM=P148-00-00,P148-00-00_0003,5649.2
     739    1331    1669    2669
River Rch & RM=P148-00-00,P148-00-00_0003,5526.2
     758    1358    1701    2713
River Rch & RM=P148-00-00,P148-00-00_0003,4744
     783    1395    1745    2775
River Rch & RM=P148-00-00,P148-00-00_0003,3682.5
     808    1433    1788    2836
River Rch & RM=P148-00-00,P148-00-00_0003,2659
     833    1470    1831    2896
River Rch & RM=P148-00-00,P148-00-00_0003,1663.8
     859    1507    1874    2956
River Rch & RM=P148-00-00,P148-00-00_0003,698.1
    1014    1736    2141    3331
Boundary for River Rch & Prof#=P148-00-00,P148-00-00_0003, 1
Up Type= 0
Dn Type= 3
Dn Slope= 0.00170
Boundary for River Rch & Prof#=P148-00-00,P148-00-00_0003, 2
Up Type= 0
Dn Type= 3
Dn Slope= 0.00170
Boundary for River Rch & Prof#=P148-00-00,P148-00-00_0003, 3
Up Type= 0
Dn Type= 3
Dn Slope= 0.00170
Boundary for River Rch & Prof#=P148-00-00,P148-00-00_0003, 4
Up Type= 0
Dn Type= 3
Dn Slope= 0.00170

--- P148-00-00.g01 (geometry) ---

Geom Title=P148-00-00 June 2007
Version=Version 3.0.1  Mar 2001

River Reach=P148-00-00      ,P148-00-00_0003
Reach XY= 30
      3082486.11     13904345.88      3085605.75       13904479.
        3085906.       13904498.      3088083.25       13904594.
      3088176.75       13904562.        3088186.       13904515.
        3088186.       13904449.      3088228.25       13904356.
        3088303.       13904342.        3088504.       13904361.
        3088967.       13904375.        3089215.       13904398.
      3089551.75       13904407.      3089590.75       13904419.
      3089614.75       13904440.       3089633.5       13904477.
      3089639.25       13904511.       3089633.5       13904565.
      3089639.25       13904589.      3089655.25       13904619.
      3089681.75       13904647.      3089697.75       13904653.
      3089715.25       13904652.      3089765.25       13904637.
      3089806.25       13904649.       3089821.5       13904649.
      3089866.25       13904631.      3090060.71     13904634.41
      3090296.64     13904735.53      3090420.22     13904808.55

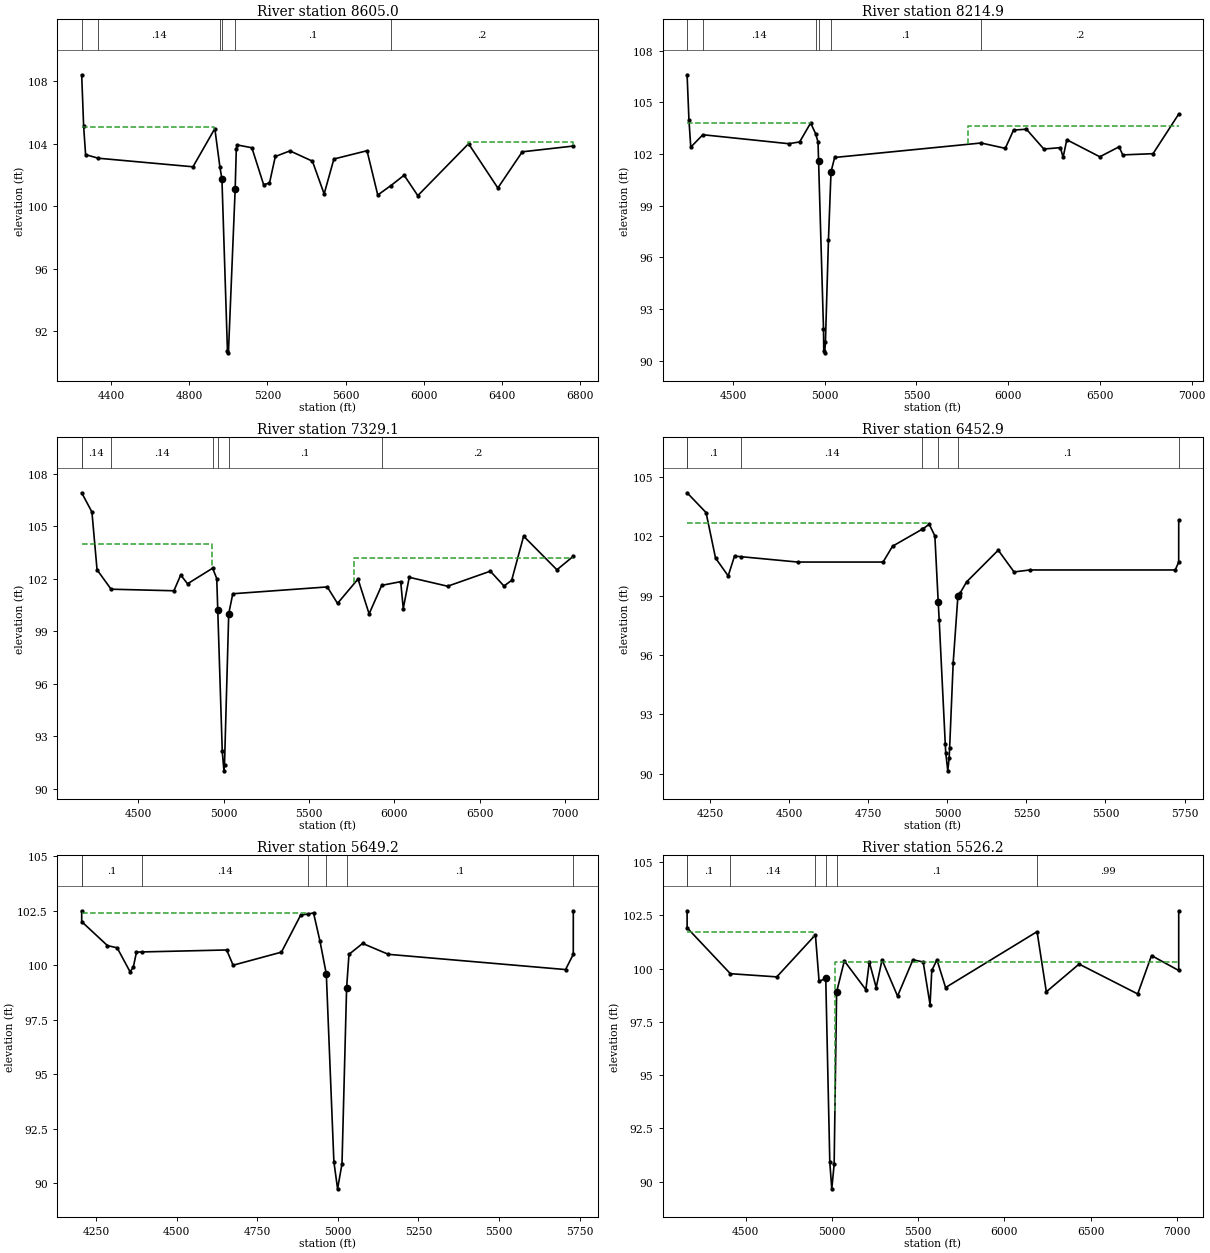
Type RM Length L Ch R = 1 ,8605.0  ,388.9,390.1,392.3
BEGIN DESCRIPTION:
Cross Section 8605.0-Interpolated
END DESCRIPTION:
XS GIS Cut Line= 5
      3082475.58       13905097.      3082486.07     13904425.31
      3082486.07     13904250.52      3082491.71     13903635.94
      3082402.12     13902583.36
#Sta/Elev= 30
  4248.8  108.43  4258.8  105.13  4268.8  103.31  4333.4  103.08  4818.8  102.53
  4930.6  104.98  4956.7  102.51    4967  101.74  4995.3    90.7  5000.2    90.6
  5034.8  101.11  5040.6  103.69  5045.6  103.93  5120.4  103.75  5180.4  101.39
  5210.4  101.48  5240.4  103.19  5315.4  103.55  5430.4  102.89  5490.4  100.79
  5540.4  103.03    5710  103.56    5765  100.72  5832.7  101.33    5900  101.99
    5970  100.68    6230  104.01    6380  101.17    6505  103.49  6766.4  103.86
#Mann= 6 , 1 , 0
  4248.8      .1       0  4333.4     .14       0  4956.7      .1       0
    4967     .04       0  5034.8      .1       0  5832.7      .2       0
#XS Ineff= 2 , 0
       0    4926  105.05    6225       0   104.1
Permanent Ineff=
       F       F
Bank Sta=4967,5034.8
XS Rating Curve= 0
Exp/Cntr=.3,.1

Type RM Length L Ch R = 1 ,8214.9  ,884.4,885.8,914
BEGIN DESCRIPTION:
Cross Section 8214.9
END DESCRIPTION:
XS GIS Cut Line= 4
      3082856.54     13905112.12       3082866.6     13904559.04
      3082900.59     13903833.98      3083140.02     13902454.53
#Sta/Elev= 30
  4250.5   106.6  4260.5     104  4270.5   102.4  4336.4  103.12  4803.7   102.6
  4863.7   102.7  4923.7   103.8  4950.5  103.19    4964   102.7    4967   101.6
  4993.8   91.85  4995.3   90.56  5000.2   90.46  5004.4   91.11  5020.8   97.01
  5034.8  100.97  5054.6   101.8  5852.6  102.64  5984.6  102.33  6029.6  103.39
  6099.6  103.44  6194.6  102.29  6284.6  102.37  6299.6  101.81  6319.6  102.83
  6499.6  101.84  6604.6  102.42  6624.6  101.95  6789.6  102.02  6929.6  104.32
#Mann= 6 , 1 , 0
  4250.5      .2       0  4336.4     .14       0  4950.5      .1       0
    4967     .04       0  5034.8      .1       0  5852.6      .2       0
#XS Ineff= 2 , 0
       0    4923   103.8  5783.5       0   103.6
Permanent Ineff=
       F       F
Bank Sta=4967,5034.8
XS Rating Curve= 0
Exp/Cntr=.3,.1

Type RM Length L Ch R = 1 ,7329.1  ,905.1,876.2,874.3
BEGIN DESCRIPTION:
Cross Section 7329.1
END DESCRIPTION:
XS GIS Cut Line= 3
      3083670.97     13905227.46      3083784.27     13904185.18
      3083346.28     13902407.33
#Sta/Elev= 30
  4168.2   106.9  4228.2   105.8  4258.2   102.5  4340.3  101.39  4708.2   101.3
  4748.2   102.2  4788.2   101.7  4935.1  102.59  4959.2     102  4965.2   100.2
  4991.5   92.13  5001.3   91.01  5004.7   91.35  5029.4   99.99  5053.2  101.13
  5606.6  101.52  5666.6  100.58  5786.6  101.97  5851.6   99.98  5925.5  101.61
  6036.6  101.82  6051.6  100.28  6086.6  102.07  6311.6  101.56  6561.6  102.42
  6641.6  101.57  6686.6   101.9  6756.6  104.42  6951.6   102.5  7047.6  103.27
#Mann= 7 , 1 , 0
  4168.2      .2       0  4168.2     .14       0  4340.3     .14       0
  4935.1      .1       0  4965.2     .04       0  5029.4      .1       0
  5925.5      .2       0
#XS Ineff= 2 , 0
       0    4934     104  5765.6       0   103.2
Permanent Ineff=
       F       F
Bank Sta=4965.2,5029.4
XS Rating Curve= 0
Exp/Cntr=.3,.1

Type RM Length L Ch R = 1 ,6452.9  ,812,803.7,780
BEGIN DESCRIPTION:
Cross Section 6452.9
END DESCRIPTION:
XS GIS Cut Line= 5
      3084602.41     13905260.79      3084636.26     13904437.96
      3084636.31      13904437.6      3084645.28     13904377.78
      3084693.42      13903708.6
#Sta/Elev= 30
  4176.3   104.2  4236.3   103.2  4266.3   100.9  4306.3     100  4326.3     101
  4347.4  100.97  4526.3   100.7  4796.3   100.7  4826.3   101.5  4920.2  102.36
  4923.6  102.39  4942.3  102.61  4960.2  102.02  4970.7    98.7  4973.8   97.79
  4993.1   91.51  4994.6   91.06  5001.1   90.15  5005.4   90.81  5006.9    91.3
  5018.2   95.62  5033.1   98.98  5040.7   99.15  5060.7    99.7  5160.7   101.3
  5210.7   100.2  5260.7   100.3  5720.7   100.3  5731.6   100.7  5731.7   102.8
#Mann= 7 , 1 , 0
  4176.3      .2       0  4176.3      .1       0  4347.4     .14       0
  4920.2      .1       0  4970.7     .04       0  5033.1      .1       0
  5731.6      .2       0
#XS Ineff= 2 , 0
       0    4940  102.65               0
Permanent Ineff=
       F       F
Bank Sta=4970.7,5033.1
XS Rating Curve= 0
Exp/Cntr=.3,.1

Type RM Length L Ch R = 1 ,5649.2  ,115.4,123,200.8
BEGIN DESCRIPTION:
Cross Section 5649.2-Interpolated
END DESCRIPTION:
XS GIS Cut Line= 4
      3085426.38     13905267.22       3085439.2     13904587.69
       3085439.2     13904395.37      3085452.02     13903741.48
#Sta/Elev= 26
  4204.5   102.5  4204.6     102  4284.6   100.9  4314.6   100.8  4354.6    99.7
  4364.6    99.9  4374.6   100.6  4392.6  100.61  4654.6   100.7  4674.6     100
  4824.6   100.6  4884.3   102.3  4906.2  102.35  4924.3   102.4  4944.3   101.1
  4963.9    99.6  4987.4   90.98  4998.9   89.73  5012.6   90.88  5026.9   98.96
  5034.3   100.5  5076.6     101  5156.6   100.5  5706.6    99.8  5730.6   100.5
  5730.7   102.5
#Mann= 7 , 1 , 0
  4204.5      .2       0  4204.6      .1       0  4392.6     .14       0
  4906.2      .1       0  4963.9     .04       0  5026.9      .1       0
  5730.6      .2       0
#XS Ineff= 2 , 0
       0    4907   102.4               0
Permanent Ineff=
       F       F
Bank Sta=4963.9,5026.9
XS Rating Curve= 0
Exp/Cntr=.5,.3

Type RM Length L Ch R = 1 ,5526.2  ,117,117,117
BEGIN DESCRIPTION:
Upstream Section of Bridge/Culvert/Weir
END DESCRIPTION:
XS GIS Cut Line= 6
      3085512.04      13905314.6      3085561.43     13904281.18
      3085678.73     13904023.44      3086131.46     13903604.42
      3086198.86     13903435.94      3086238.14     13902709.82
#Sta/Elev= 30
  4159.8  102.71  4159.9  101.91  4410.7   99.76  4679.9   99.61    4904  101.58
  4925.3    99.4  4963.9   99.54  4987.4   90.92  4998.9   89.67  5012.6   90.82
  5026.9    98.9  5071.6  100.36  5196.5   99.01  5216.5  100.31  5256.5   99.11
  5290.4  100.41  5380.4   98.71  5469.4  100.41  5528.8  100.31  5568.8   98.31
  5578.8   99.91  5608.8  100.41  5658.8   99.11  6189.4  101.73  6243.1   98.91
  6433.1  100.21  6773.1   98.81  6853.1  100.61  7010.8   99.91  7010.9  102.71
#Mann= 7 , 1 , 0
  4159.8      .2       0  4159.9      .1       0  4410.7     .14       0
    4904      .1       0  4963.9     .04       0  5026.9      .1       0
  6189.4     .99       0
#XS Ineff= 2 , 0
       0    4892   101.7    5017       0   100.3
Permanent Ineff=
       F       F
Bank Sta=4963.9,5026.9
XS Rating Curve= 0
Exp/Cntr=.5,.3

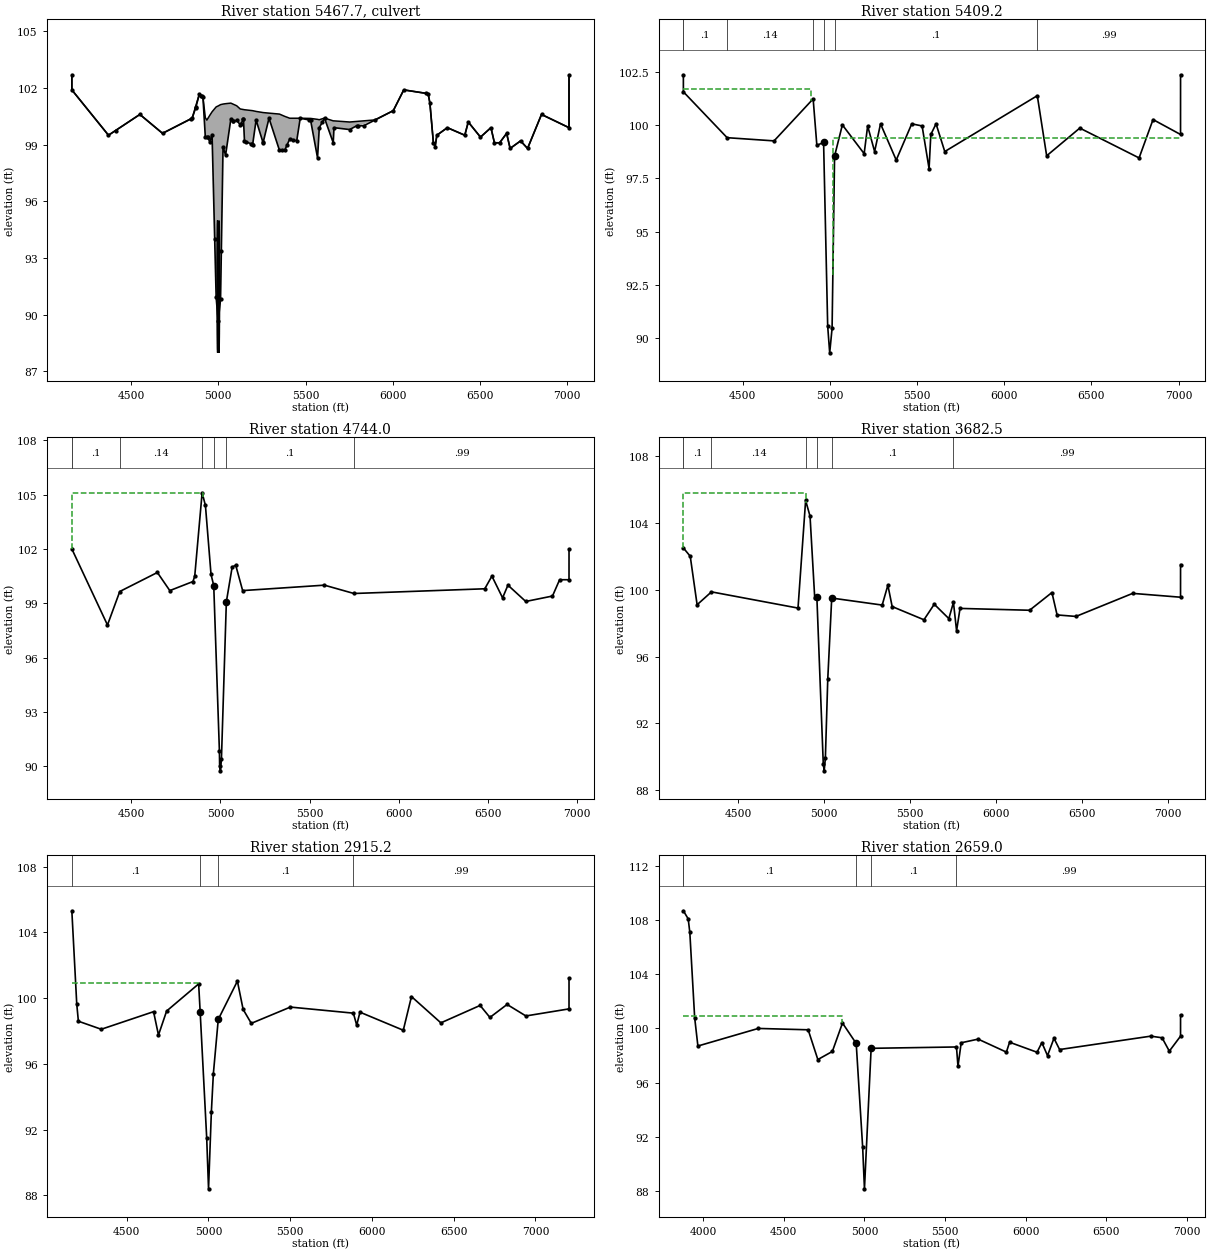
Type RM Length L Ch R = 2 ,5467.7  ,,,
BEGIN DESCRIPTION:
ANNE LOUISE ROAD
Structure ID: P48-3
END DESCRIPTION:
Bridge Culvert--1,0,-1,-1, 0
Deck Dist Width WeirC Skew NumUp NumDn MinLoCord MaxHiCord MaxSubmerge Is_Ogee
10,97,3,0, 60, 60, , , .95, 0, 1,1,,
  4159.8  4159.9  4369.9  4549.9  4679.9  4849.9  4891.3  4911.7  4925.3  4933.9
  4951.3  4963.9  4987.4  4998.9  5012.6  5026.9  5041.4  5071.6  5105.1  5125.5
    5144  5149.7  5196.5  5216.5  5256.5  5290.4  5350.4  5380.4  5409.4  5449.4
  5469.4  5528.8  5568.8  5578.8  5608.8  5658.8  5663.1  5753.1  5897.3  6003.1
  6063.1  6203.1  6213.1  6233.1  6243.1  6253.1  6313.1  6413.1  6433.1  6503.1
  6563.1  6583.1  6613.1  6653.1  6673.1  6733.1  6773.1  6853.1  7010.8  7010.9
   102.7   101.9    99.5   100.6    99.6  100.41  101.69  101.52  100.43   100.3
  100.56  100.74     101  101.05  101.12  101.15  101.17   101.2  101.06  100.89
  100.86  100.85   100.8  100.76   100.7  100.67  100.62   100.5   100.4   100.4
   100.4  100.39  100.34  100.32  100.41  100.26  100.26   100.2  100.31   100.8
   101.9   101.7   101.2    99.1    98.9    99.5    99.9    99.5   100.2    99.4
    99.9    99.1    99.1    99.6    98.8    99.2    98.8   100.6    99.9   102.7
   102.7   101.9    99.5   100.6    99.6   100.4  101.68  101.51   99.39    99.4
   99.14   99.53   90.91   89.66   90.81   98.89   98.44  100.35  100.29  100.05
  100.34    99.2      99   100.3    99.1   100.4    98.7    98.7    99.3    99.2
   100.4   100.3    98.3    99.9   100.4    99.1    99.9    99.8   100.3   100.8
   101.9   101.7   101.2    99.1    98.9    99.5    99.9    99.5   100.2    99.4
    99.9    99.1    99.1    99.6    98.8    99.2    98.8   100.6    99.9   102.7
  4159.8  4159.9  4369.9  4549.9  4679.9  4849.9  4891.3  4911.7  4925.3  4933.9
  4951.3  4963.9  4987.4  4998.9  5012.6  5026.9  5041.4  5071.6  5105.1  5125.5
    5144  5149.7  5196.5  5216.5  5256.5  5290.4  5350.4  5380.4  5409.4  5449.4
  5469.4  5528.8  5568.8  5578.8  5608.8  5658.8  5663.1  5753.1  5897.3  6003.1
  6063.1  6203.1  6213.1  6233.1  6243.1  6253.1  6313.1  6413.1  6433.1  6503.1
  6563.1  6583.1  6613.1  6653.1  6673.1  6733.1  6773.1  6853.1  7010.8  7010.9
   102.7   101.9    99.5   100.6    99.6  100.41  101.69  101.52  100.43   100.3
  100.56  100.74     101  101.05  101.12  101.15  101.17   101.2  101.06  100.89
  100.86  100.85   100.8  100.76   100.7  100.67  100.62   100.5   100.4   100.4
   100.4  100.39  100.34  100.32  100.41  100.26  100.26   100.2  100.31   100.8
   101.9   101.7   101.2    99.1    98.9    99.5    99.9    99.5   100.2    99.4
    99.9    99.1    99.1    99.6    98.8    99.2    98.8   100.6    99.9   102.7
  102.34  101.54   99.14  100.24   99.24  100.04  101.32  101.15   99.03   99.04
   98.78   99.17   90.55    89.3   90.45   98.53   98.08   99.99   99.93   99.69
   99.98   98.84   98.64   99.94   98.74  100.04   98.34   98.34   98.94   98.84
  100.04   99.94   97.94   99.54  100.04   98.74   99.54   99.44   99.94  100.44
  101.54  101.34  100.84   98.74   98.54   99.14   99.54   99.14   99.84   99.04
   99.54   98.74   98.74   99.24   98.44   98.84   98.44  100.24   99.54  102.34
BR Coef= 1 , 0 , 0 ,1.25, 0 ,,,.8,-1,2,0,
WSPro=,,,, 1 ,,,, 0 ,,,, 0 ,,,,-1 ,-1 ,-1 , 0 , 0 , 0 , 0 , 0
Culvert=1,7,,97,.024,.7,1,1,3,87.99,4995.4,87.68,4995.4,Culvert #1  , 0 ,10
Culvert Bottom n=.024
Culvert=1,7,,97,.024,.7,1,1,3,87.98,5003.8,87.57,5003.8,Culvert #2  , 0 ,10
Culvert Bottom n=.024
BR U #Sta/Elev= 86
  4159.8   102.7  4159.9   101.9  4369.9    99.5  4410.7   99.75  4549.9   100.6
  4679.9    99.6  4842.3  100.36  4849.9   100.4  4869.8  100.95  4871.4     101
  4891.3  101.68  4901.1   101.6    4904  101.57  4911.7  101.51  4925.3   99.39
  4933.9    99.4  4938.1   99.41  4951.3   99.14  4963.9   99.53  4978.9   94.03
  4987.4   90.91  4998.9   89.66  5012.6   90.81  5017.1   93.35  5026.9   98.89
  5041.4   98.44  5071.6  100.35  5083.3  100.25  5084.5  100.25  5105.1  100.29
  5125.5  100.05  5129.8  100.12  5143.8  100.34    5144  100.34  5149.7    99.2
  5158.2   99.16  5184.7   99.05  5194.8   99.01  5196.5      99  5216.5   100.3
  5254.8   99.15  5256.5    99.1  5290.4   100.4  5350.4    98.7  5367.8    98.7
  5380.4    98.7  5392.9   98.96  5409.4    99.3  5425.9   99.26  5449.4    99.2
  5469.4   100.4  5520.3  100.31  5528.8   100.3  5568.8    98.3  5578.8    99.9
  5595.6  100.18  5608.8   100.4  5658.8    99.1  5663.1    99.9  5753.1    99.8
  5793.1     100  5803.1     100  5833.1     100  5897.3   100.3  6003.1   100.8
  6063.1   101.9  6189.4  101.72  6203.1   101.7  6213.1   101.2  6233.1    99.1
  6243.1    98.9  6253.1    99.5  6313.1    99.9  6413.1    99.5  6433.1   100.2
  6503.1    99.4  6563.1    99.9  6583.1    99.1  6613.1    99.1  6653.1    99.6
  6673.1    98.8  6733.1    99.2  6773.1    98.8  6853.1   100.6  7010.8    99.9
  7010.9   102.7
BR U #Mann= 7
  4159.8      .2  4159.9      .1  4410.7     .14    4904      .1  4963.9     .04
  5026.9      .1  6189.4     .99
BR U Banks=4963.9,5026.9
BR D #Sta/Elev= 86
  4159.8  102.34  4159.9  101.54  4369.9   99.14  4410.7   99.39  4549.9  100.24
  4679.9   99.24  4842.3     100  4849.9  100.04  4869.8  100.59  4871.4  100.64
  4891.3  101.32  4901.1  101.24    4904  101.21  4911.7  101.15  4925.3   99.03
  4933.9   99.04  4938.1   99.05  4951.3   98.78  4963.9   99.17  4978.9   93.67
  4987.4   90.55  4998.9    89.3  5012.6   90.45  5017.1   92.99  5026.9   98.53
  5041.4   98.08  5071.6   99.99  5083.3   99.89  5084.5   99.89  5105.1   99.93
  5125.5   99.69  5129.8   99.76  5143.8   99.98    5144   99.98  5149.7   98.84
  5158.2    98.8  5184.7   98.69  5194.8   98.65  5196.5   98.64  5216.5   99.94
  5254.8   98.79  5256.5   98.74  5290.4  100.04  5350.4   98.34  5367.8   98.34
  5380.4   98.34  5392.9    98.6  5409.4   98.94  5425.9    98.9  5449.4   98.84
  5469.4  100.04  5520.3   99.95  5528.8   99.94  5568.8   97.94  5578.8   99.54
  5595.6   99.82  5608.8  100.04  5658.8   98.74  5663.1   99.54  5753.1   99.44
  5793.1   99.64  5803.1   99.64  5833.1   99.64  5897.3   99.94  6003.1  100.44
  6063.1  101.54  6189.4  101.36  6203.1  101.34  6213.1  100.84  6233.1   98.74
  6243.1   98.54  6253.1   99.14  6313.1   99.54  6413.1   99.14  6433.1   99.84
  6503.1   99.04  6563.1   99.54  6583.1   98.74  6613.1   98.74  6653.1   99.24
  6673.1   98.44  6733.1   98.84  6773.1   98.44  6853.1  100.24  7010.8   99.54
  7010.9  102.34
BR D #Mann= 7
  4159.8      .2  4159.9      .1  4410.7     .14    4904      .1  4963.9     .04
  5026.9      .1  6189.4     .99
BR D Banks=4963.9,5026.9
BC Design=,, 0 ,, 0 ,,,,,,

Type RM Length L Ch R = 1 ,5409.2  ,665.2,665.2,665.2
BEGIN DESCRIPTION:
Downstream Section of Bridge/Culvert/Weir
END DESCRIPTION:
XS GIS Cut Line= 6
       3085628.8     13905321.99      3085678.19     13904288.56
      3085795.49     13904030.82      3086248.22      13903611.8
      3086315.62     13903443.32       3086354.9     13902717.21
#Sta/Elev= 30
  4159.8  102.35  4159.9  101.55  4410.7    99.4  4679.9   99.25    4904  101.22
  4925.3   99.04  4963.9   99.18  4987.4   90.56  4998.9   89.31  5012.6   90.46
  5026.9   98.54  5071.6     100  5196.5   98.65  5216.5   99.95  5256.5   98.75
  5290.4  100.05  5380.4   98.35  5469.4  100.05  5528.8   99.95  5568.8   97.95
  5578.8   99.55  5608.8  100.05  5658.8   98.75  6189.4  101.37  6243.1   98.55
  6433.1   99.85  6773.1   98.45  6853.1  100.25  7010.8   99.55  7010.9  102.35
#Mann= 7 , 1 , 0
  4159.8      .2       0  4159.9      .1       0  4410.7     .14       0
    4904      .1       0  4963.9     .04       0  5026.9      .1       0
  6189.4     .99       0
#XS Ineff= 2 , 0
       0    4892   101.7    5017       0    99.4
Permanent Ineff=
       F       F
Bank Sta=4963.9,5026.9
XS Rating Curve= 0
Exp/Cntr=.5,.3

Type RM Length L Ch R = 1 ,4744.0  ,1125.9,1061.5,1057.2
BEGIN DESCRIPTION:
Cross Section 4744.0
END DESCRIPTION:
XS GIS Cut Line= 5
      3086174.06     13905331.94      3086305.99     13904818.89
      3086354.85     13904423.11      3086345.07     13903934.48
      3086434.26     13902564.59
#Sta/Elev= 30
  4166.2     102  4366.2    97.8  4435.2   99.65  4646.2   100.7  4715.9    99.7
  4845.9   100.2  4855.9   100.5  4897.3   105.1  4915.9   104.4  4947.3  100.59
  4962.5   99.98  4994.3   90.85  4995.6   90.02  5000.2   89.75  5005.7    90.4
  5033.3   99.08  5065.9     101  5085.9   101.1  5124.7    99.7  5583.5     100
  5749.2   99.54  6483.5    99.8  6523.5   100.5  6583.5    99.3  6613.5     100
  6713.5    99.1  6863.5    99.4  6903.5   100.3  6956.2   100.3  6956.3     102
#Mann= 7 , 1 , 0
  4166.2      .2       0  4166.2      .1       0  4435.2     .14       0
  4897.3      .1       0  4962.5     .04       0  5033.3      .1       0
  5749.2     .99       0
#XS Ineff= 2 , 0
       0    4903   105.1               0
Permanent Ineff=
       F       F
Bank Sta=4962.5,5033.3
XS Rating Curve= 0
Exp/Cntr=.3,.1

Type RM Length L Ch R = 1 ,3682.5  ,906.3,767.3,506.3
BEGIN DESCRIPTION:
Cross Section 3682.5
END DESCRIPTION:
XS GIS Cut Line= 6
      3087380.95     13905375.92      3087424.93      13905170.7
       3087434.7     13904843.32       3087400.5      13904638.1
      3087429.81     13903968.69       3087390.7     13902490.54
#Sta/Elev= 30
  4180.3   102.5  4220.3     102  4260.3    99.1  4343.9   99.87  4847.7    98.9
    4892  105.34  4917.7   104.4  4944.9   99.52  4957.3   99.59  4994.7   89.59
    5000   89.16    5007   89.93  5020.8   94.63  5043.9    99.5  5337.7   99.08
  5370.8  100.27  5395.8   98.99  5580.8    98.2  5640.8   99.13  5725.8   98.27
  5752.5   99.24  5770.8   97.54  5790.8   98.88  6195.8   98.77  6325.8   99.83
  6355.8   98.49  6465.8    98.4  6795.8   99.78  7074.5   99.55  7074.6   101.5
#Mann= 7 , 1 , 0
  4180.3      .2       0  4180.3      .1       0  4343.9     .14       0
    4892      .1       0  4957.3     .04       0  5043.9      .1       0
  5752.5     .99       0
#XS Ineff= 2 , 0
       0    4896   105.8               0
Permanent Ineff=
       F       F
Bank Sta=4957.3,5043.9
XS Rating Curve= 0
Exp/Cntr=.3,.1

Type RM Length L Ch R = 1 ,2915.2  ,353.3,256.2,252.9
BEGIN DESCRIPTION:
Cross Section 2915.2-Interpolated
END DESCRIPTION:
XS GIS Cut Line= 6
      3088425.87     13905355.13       3088242.8     13904683.85
      3088120.79      13904498.2      3087847.41      13904214.3
      3087726.06     13903933.68      3087591.26     13902516.15
#Sta/Elev= 30
    4164  105.32    4194   99.65    4204    98.6    4344   98.11    4664   99.18
    4694   97.76    4744   99.22  4939.8  100.87  4949.2   99.15  4989.1   91.49
  5000.3    88.4  5017.6   93.08  5029.8    95.4  5059.8   98.71  5176.9  101.04
  5211.9   99.32  5261.9   98.47    5501   99.46  5886.5   99.09  5906.8   98.36
  5926.8   99.15  6191.8   98.05  6241.8   100.1  6421.8    98.5  6661.8   99.56
  6721.8   98.83  6826.8   99.62  6941.8   98.92  7205.7   99.35  7205.8   101.2
#Mann= 4 , 1 , 0
    4164      .1       0  4949.2     .04       0  5059.8      .1       0
  5886.5     .99       0
#XS Ineff= 2 , 0
       0  4939.6   100.9               0
Permanent Ineff=
       F       F
Bank Sta=4949.2,5059.8
XS Rating Curve= 0
Exp/Cntr=.3,.1

Type RM Length L Ch R = 1 ,2659.0  ,912.9,995.2,1021.8
BEGIN DESCRIPTION:
Cross Section 2659.0
END DESCRIPTION:
XS GIS Cut Line= 6
       3088499.9     13905395.46      3088490.12     13904931.27
      3088495.01     13904682.07      3088333.76      13904462.2
      3088152.97     13904203.23       3087599.8     13902511.88
#Sta/Elev= 30
  3877.9   108.7  3907.9   108.1  3917.9   107.1  3947.9   100.8  3967.9    98.7
  4342.2     100  4651.4    99.9  4711.4    97.7  4801.4    98.3  4864.1   100.4
  4949.2   98.89  4989.1   91.23  5000.3   88.14  5041.7   98.53  5570.7   98.63
  5579.9    97.2  5599.9   98.94  5704.9   99.21  5879.9   98.25  5899.9   98.98
  6069.9   98.24  6099.9   98.95  6134.9   97.99  6174.9   99.27  6209.9   98.44
  6774.9   99.43  6844.9   99.31  6889.9   98.32  6959.4   99.43  6959.5     101
#Mann= 5 , 1 , 0
  3877.9      .2       0  3877.9      .1       0  4949.2     .04       0
  5041.7      .1       0  5570.7     .99       0
#XS Ineff= 2 , 0
       0    4864   100.9               0
Permanent Ineff=
       F       F
Bank Sta=4949.2,5041.7
XS Rating Curve= 0
Exp/Cntr=.3,.1

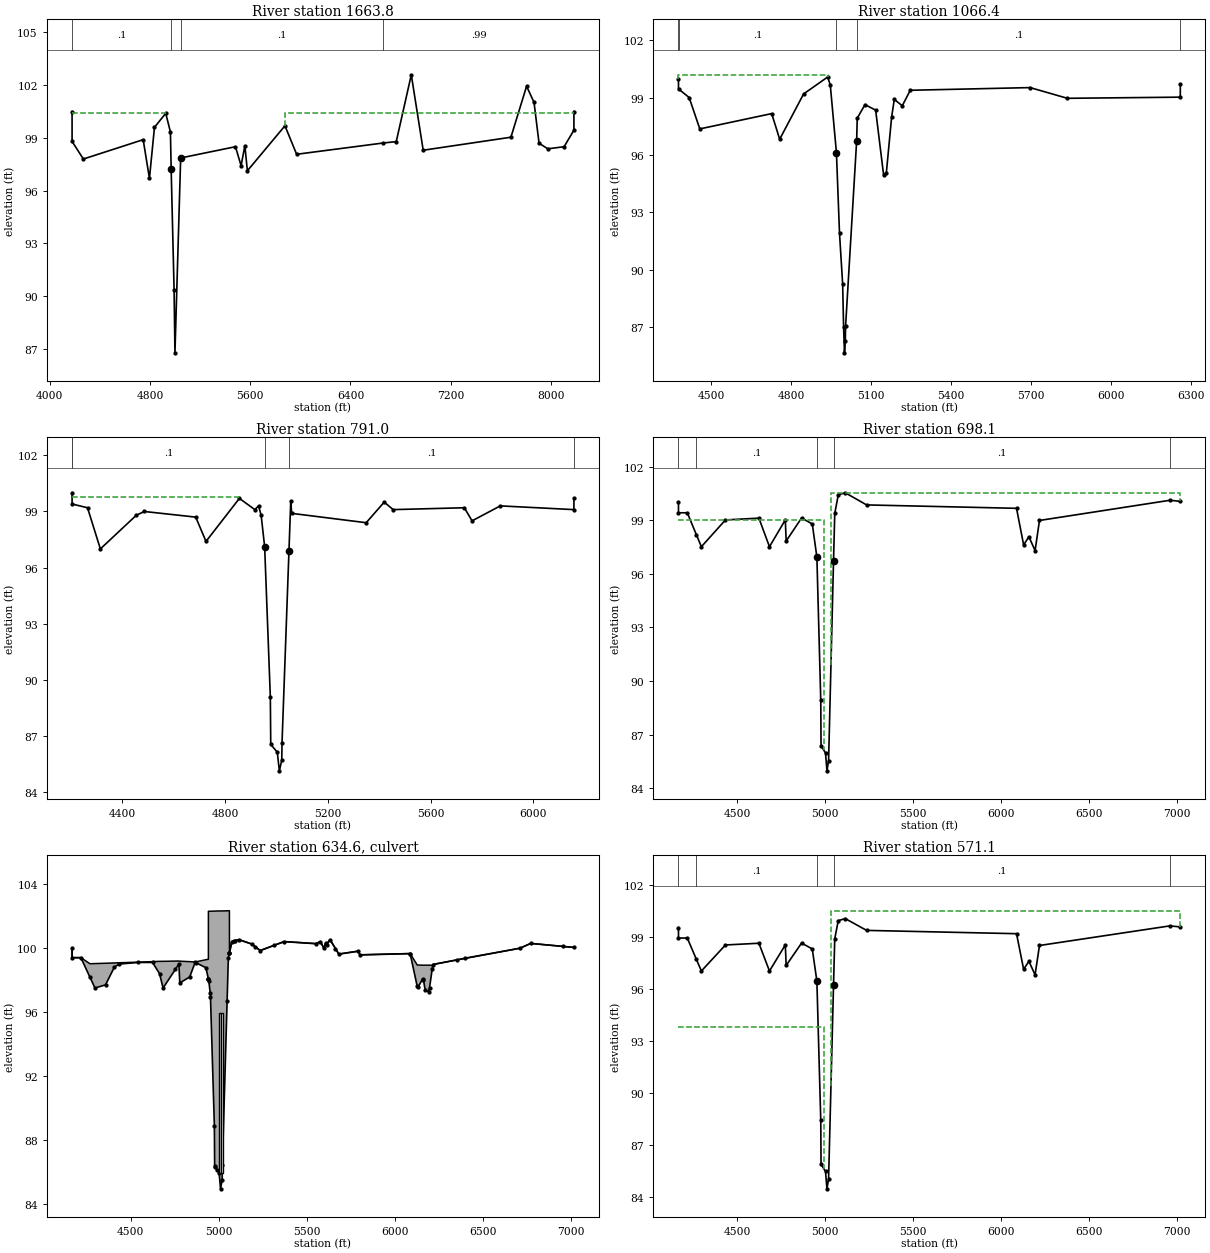
Type RM Length L Ch R = 1 ,1663.8  ,558.7,597.4,592.6
BEGIN DESCRIPTION:
Cross Section 1663.8
END DESCRIPTION:
XS GIS Cut Line= 6
      3089208.98     13905219.22      3089218.17     13904901.95
      3089252.37     13904276.52      3088915.22     13903580.86
      3088541.82     13901703.21      3088221.77     13901511.18
#Sta/Elev= 30
  4178.7   100.5  4178.8    98.8  4268.8    97.8  4746.1    98.9  4796.1    96.7
  4836.1    99.6  4926.1   100.4  4963.5   99.34  4969.4   97.24  4992.7   90.38
  4999.6   86.78  5045.3   97.86  5482.5    98.5  5527.5   97.42  5557.5   98.56
  5577.5   97.13  5877.5   99.69  5970.6   98.07  6660.3   98.71  6765.6   98.79
  6885.6  102.59  6980.6    98.3  7680.6   99.04  7805.6  101.94    7865  101.02
    7905    98.7    7975   98.38    8105    98.5  8183.2   99.44  8183.3   100.5
#Mann= 4 , 1 , 0
  4178.7      .1       0  4969.4     .04       0  5045.3      .1       0
  6660.3     .99       0
#XS Ineff= 2 , 0
       0    4926   100.4    5874       0   100.4
Permanent Ineff=
       F       F
Bank Sta=4969.4,5045.3
XS Rating Curve= 0
Exp/Cntr=.3,.1

Type RM Length L Ch R = 1 ,1066.4  ,283.9,275.4,239.5
BEGIN DESCRIPTION:
Cross Section 1066.4-Interpolated
END DESCRIPTION:
XS GIS Cut Line= 4
      3089383.25     13905193.08      3089653.78     13904678.55
      3089717.43     13904577.76      3090261.93     13903526.03
#Sta/Elev= 30
  4376.1     100  4376.2   99.46  4416.2   99.01  4456.2   97.37  4726.2   98.17
  4756.2   96.83  4846.2    99.2  4936.2  100.08  4946.2   99.68  4969.4   96.12
  4980.9   91.92  4992.7   89.26  4996.3      87  4999.6   85.66  5002.7   86.29
  5003.7   87.04  5045.3   96.74  5047.5   97.93  5076.7   98.64  5116.7   98.35
  5146.7   94.94  5156.7   95.05  5176.7   97.99  5186.7   98.91  5216.7   98.58
  5246.7   99.39  5696.7   99.53  5836.7   98.97  6260.9   99.03    6261    99.7
#Mann= 5 , 1 , 0
  4376.1      .2       0  4376.2      .1       0  4969.4     .04       0
  5045.3      .1       0  6260.9      .2       0
#XS Ineff= 2 , 0
       0    4936   100.2               0
Permanent Ineff=
       F       F
Bank Sta=4969.4,5045.3
XS Rating Curve= 0
Exp/Cntr=.3,.1

Type RM Length L Ch R = 1 ,791.0   ,59.1,92.9,129.5
BEGIN DESCRIPTION:
Cross Section 791.0-Interpolated
END DESCRIPTION:
XS GIS Cut Line= 6
      3089429.21     13905192.46      3089679.52     13905064.65
      3089935.16     13904713.14      3089937.84     13904209.83
      3090036.35     13903994.16      3090307.96     13903578.75
#Sta/Elev= 30
  4204.8     100  4204.9    99.4  4264.9    99.2  4314.9      97  4454.9    98.8
    4486      99    4686    98.7    4726    97.4    4856    99.7    4916    99.1
  4930.6    99.3  4940.6    98.8 4954.33   97.11 4976.42   89.08 4977.99   86.55
 5003.39   86.14 5011.57   85.14 5020.88   85.71 5021.92   86.65 5048.89   96.89
 5055.85   99.55  5059.5    98.9  5349.5    98.4  5419.5    99.5  5454.4    99.1
  5731.5    99.2  5761.5    98.5  5871.5    99.3  6157.8    99.1  6157.9    99.7
#Mann= 5 , 1 , 0
  4204.8      .2       0  4204.9      .1       0 4954.33     .04       0
 5048.89      .1       0  6157.8      .2       0
#XS Ineff= 2 , 0
       0    4855   99.75               0
Permanent Ineff=
       F       F
Bank Sta=4954.33,5048.89
XS Rating Curve= 0
Exp/Cntr=.5,.3

Type RM Length L Ch R = 1 ,698.1   ,127,127,127
BEGIN DESCRIPTION:
Upstream Section of Bridge/Culvert/Weir
END DESCRIPTION:
XS GIS Cut Line= 3
      3089545.07      13905293.3      3090123.42     13904513.07
      3091218.23     13902984.38
#Sta/Elev= 30
  4167.9  100.02    4168   99.42    4218   99.42  4269.3    98.2    4298   97.52
  4434.9   99.02  4624.9   99.12  4684.9   97.52  4774.9   99.02 4779.89   97.84
 4867.41   99.13 4928.23   98.79 4954.33   96.94 4976.42   88.91 4977.99   86.38
 5003.39   85.97 5011.57   84.97 5020.88   85.54 5048.89   96.72 5055.85   99.38
 5075.78  100.42 5115.54  100.54 5236.99   99.86  6088.7   99.67  6129.1   97.62
  6159.1   98.08  6194.1    97.3  6219.1   98.99  6960.1  100.12  7019.4  100.06
#Mann= 5 , 1 , 0
  4167.9      .2       0  4269.3      .1       0 4954.33     .04       0
 5048.89      .1       0  6960.1      .2       0
#XS Ineff= 2 , 0
       0    4993      99  5034.3       0   100.5
Permanent Ineff=
       F       F
Bank Sta=4954.33,5048.89
XS Rating Curve= 0
Exp/Cntr=.5,.3

Type RM Length L Ch R = 2 ,634.6   ,,,
BEGIN DESCRIPTION:
VETERANS MEMORIAL DRIVE, SKEW ANGLE OF 30 DEGREES
Structure ID: P48-01
END DESCRIPTION:
Bridge Culvert--1,0,-1,-1, 0
Deck Dist Width WeirC Skew NumUp NumDn MinLoCord MaxHiCord MaxSubmerge Is_Ogee
10,107,3,0, 57, 57, , , .95, 0, 1,1,,
  4167.9    4168    4218  4269.3    4298    4358    4408  4434.9  4624.9  4664.9
  4684.9  4774.9 4779.89 4836.18 4867.41 4928.23 4942.39  4942.5 4944.76 4952.85
 4954.33 4976.42 4977.99 5003.39 5011.57 5020.88 5021.92 5055.85    5062 5062.11
 5075.78 5115.54 5188.44 5236.99    5373  5553.7  5578.7  5598.7  5608.7  5613.7
  5633.7  5683.7  5793.7  5803.7  6088.7  6129.1  6134.1  6159.1  6164.1  6174.1
  6194.1  6199.1  6214.1  6219.1  6713.1  6773.8  7019.4
     100    99.4    99.4   99.02   99.03   99.05   99.07   99.08   99.15   99.17
   99.17   99.19   99.18   99.15   99.13   99.27    99.3   102.3   102.3   102.3
   102.3  102.31  102.31  102.32  102.32  102.32  102.32  102.33  102.33    99.7
  100.41  100.53  100.26   99.85  100.41  100.28  100.41     100   100.3  100.23
  100.53   99.63   99.81   99.58   99.66   98.94   98.94   98.93   98.93   98.93
   98.93   98.93   98.92   98.98   99.99  100.29  100.04
     100    99.4    99.4   98.18    97.5    97.7    98.8      99    99.1    98.4
    97.5      99   97.82   98.19   99.11   98.77   98.08   98.07   97.96   97.19
   96.92   88.89   86.36   85.95   84.95   85.52   86.46   99.36   99.68   99.69
   100.4  100.52  100.25   99.84   100.4  100.27   100.4   99.99  100.29  100.22
  100.52   99.62    99.8   99.57   99.65    97.6   97.56   98.06   98.03   97.38
   97.28   97.52   98.69   98.97   99.99  100.29  100.04
  4167.9    4168    4218  4269.3    4298    4358    4408  4434.9  4624.9  4664.9
  4684.9  4774.9 4779.89 4836.18 4867.41 4928.23 4942.39  4942.5 4944.76 4952.85
 4954.33 4976.42 4977.99 5003.39 5011.57 5020.88 5021.92 5055.85    5062 5062.11
 5075.78 5115.54 5188.44 5236.99    5373  5553.7  5578.7  5598.7  5608.7  5613.7
  5633.7  5683.7  5793.7  5803.7  6088.7  6129.1  6134.1  6159.1  6164.1  6174.1
  6194.1  6199.1  6214.1  6219.1  6713.1  6773.8  7019.4
     100    99.4    99.4   99.02   99.03   99.05   99.07   99.08   99.15   99.17
   99.17   99.19   99.18   99.15   99.13   99.27    99.3   102.3   102.3   102.3
   102.3  102.31  102.31  102.32  102.32  102.32  102.32  102.33  102.33    99.7
  100.41  100.53  100.26   99.85  100.41  100.28  100.41     100   100.3  100.23
  100.53   99.63   99.81   99.58   99.66   98.94   98.94   98.93   98.93   98.93
   98.93   98.93   98.92   98.98   99.99  100.29  100.04
   99.55   98.95   98.95   97.73   97.05   97.25   98.35   98.55   98.65   97.95
   97.05   98.55   97.37   97.74   98.66   98.32   97.63   97.62   97.51   96.74
   96.47   88.44   85.91    85.5    84.5   85.07   86.01   98.91   99.23   99.24
   99.95  100.07    99.8   99.39   99.95   99.82   99.95   99.54   99.84   99.77
  100.07   99.17   99.35   99.12    99.2   97.15   97.11   97.61   97.58   96.93
   96.83   97.07   98.24   98.52   99.54   99.84   99.59
BR Coef= 1 , 0 , 0 ,1.25, 0 ,,,.8,-1,2,0,
WSPro=,,,, 1 ,,,, 0 ,,,, 0 ,,,,-1 ,-1 ,-1 , 0 , 0 , 0 , 0 , 0
Culvert=2,10,10,107,.015,.4,1,8,1,85.92,5008,85.68,5008,Culvert #1  , 0 ,10
Culvert Bottom n=.015
Culvert=2,10,10,107,.015,.4,1,8,1,85.92,5019.2,85.68,5019.2,Culvert #2  , 0 ,10
Culvert Bottom n=.015
BR U #Sta/Elev= 74
  4167.9     100    4168    99.4    4218    99.4  4269.3   98.18    4298    97.5
    4358    97.7    4408    98.8  4434.9      99  4544.9    99.1  4624.9    99.1
  4664.9    98.4  4684.9    97.5  4754.6   98.66  4774.9      99 4779.89   97.82
 4836.18   98.19 4867.41   99.11  4870.6   99.09 4928.23   98.77 4942.39   98.08
  4942.5   98.07 4942.61   98.07 4944.76   97.96 4952.85   97.19 4954.33   96.92
 4976.42   88.89 4977.99   86.36  4979.3   86.34    4994    86.1 5003.39   85.95
 5011.57   84.95 5020.88   85.52 5021.92   86.46 5048.89    96.7 5055.85   99.36
 5061.89   99.68    5062   99.68 5062.11   99.69 5075.78   100.4  5086.7  100.43
  5094.7  100.46 5115.54  100.52 5188.44  100.25    5207  100.09 5236.99   99.84
  5314.5  100.16    5373   100.4  5553.7  100.27  5578.7   100.4  5598.7   99.99
  5608.7  100.29  5613.7  100.22  5633.7  100.52  5664.1   99.97  5683.7   99.62
  5793.7    99.8  5803.7   99.57  6088.7   99.65  6089.1   99.64  6129.1    97.6
  6134.1   97.56  6159.1   98.06  6164.1   98.03  6174.1   97.38  6194.1   97.28
  6199.1   97.52  6214.1   98.69  6219.1   98.97  6354.1   99.26  6398.1   99.36
  6713.1   99.99  6773.8  100.29  6960.1   100.1  7019.4  100.04
BR U #Mann= 5
  4167.9      .2  4269.3      .1 4954.33     .04 5048.89      .1  6960.1      .2
BR U Banks=4954.33,5048.89
BR D #Sta/Elev= 74
  4167.9   99.55    4168   98.95    4218   98.95  4269.3   97.73    4298   97.05
    4358   97.25    4408   98.35  4434.9   98.55  4544.9   98.65  4624.9   98.65
  4664.9   97.95  4684.9   97.05  4754.6   98.21  4774.9   98.55 4779.89   97.37
 4836.18   97.74 4867.41   98.66  4870.6   98.64 4928.23   98.32 4942.39   97.63
  4942.5   97.62 4942.61   97.62 4944.76   97.51 4952.85   96.74 4954.33   96.47
 4976.42   88.44 4977.99   85.91  4979.3   85.89    4994   85.65 5003.39    85.5
 5011.57    84.5 5020.88   85.07 5021.92   86.01 5048.89   96.25 5055.85   98.91
 5061.89   99.23    5062   99.23 5062.11   99.24 5075.78   99.95  5086.7   99.98
  5094.7  100.01 5115.54  100.07 5188.44    99.8    5207   99.64 5236.99   99.39
  5314.5   99.71    5373   99.95  5553.7   99.82  5578.7   99.95  5598.7   99.54
  5608.7   99.84  5613.7   99.77  5633.7  100.07  5664.1   99.52  5683.7   99.17
  5793.7   99.35  5803.7   99.12  6088.7    99.2  6089.1   99.19  6129.1   97.15
  6134.1   97.11  6159.1   97.61  6164.1   97.58  6174.1   96.93  6194.1   96.83
  6199.1   97.07  6214.1   98.24  6219.1   98.52  6354.1   98.81  6398.1   98.91
  6713.1   99.54  6773.8   99.84  6960.1   99.65  7019.4   99.59
BR D #Mann= 5
  4167.9      .2  4269.3      .1 4954.33     .04 5048.89      .1  6960.1      .2
BR D Banks=4954.33,5048.89
BC Design=,, 0 ,, 0 ,,,,,,

Type RM Length L Ch R = 1 ,571.1   ,257.3,257.3,257.3
BEGIN DESCRIPTION:
Downstream Section of Bridge/Culvert/Weir
END DESCRIPTION:
XS GIS Cut Line= 3
      3089659.73     13905347.91      3090238.08     13904567.67
      3091332.89     13903038.99
#Sta/Elev= 30
  4167.9   99.53    4168   98.93    4218   98.93  4269.3   97.71    4298   97.03
  4434.9   98.53  4624.9   98.63  4684.9   97.03  4774.9   98.53 4779.89   97.35
 4867.41   98.64 4928.23    98.3 4954.33   96.45 4976.42   88.42 4977.99   85.89
 5003.39   85.48 5011.57   84.48 5020.88   85.05 5048.89   96.23 5055.85   98.89
 5075.78   99.93 5115.54  100.05 5236.99   99.37  6088.7   99.18  6129.1   97.13
  6159.1   97.59  6194.1   96.81  6219.1    98.5  6960.1   99.63  7019.4   99.57
#Mann= 5 , 1 , 0
  4167.9      .2       0  4269.3      .1       0 4954.33     .04       0
 5048.89      .1       0  6960.1      .2       0
#XS Ineff= 2 , 0
       0    4993    93.8  5034.3       0   100.5
Permanent Ineff=
       F       F
Bank Sta=4954.33,5048.89
XS Rating Curve= 0
Exp/Cntr=.5,.3

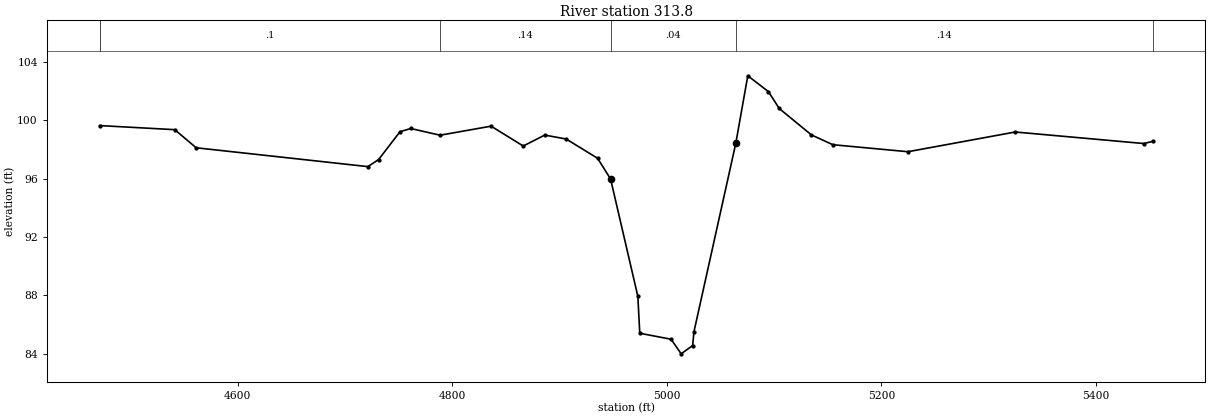
Type RM Length L Ch R = 1 ,313.8   ,0,0,0
BEGIN DESCRIPTION:
Cross Section 313.8-Interpolated
END DESCRIPTION:
XS GIS Cut Line= 5
      3089956.99     13905092.79      3090196.96     13904904.71
      3090320.19     13904839.85      3090456.39     13904723.11
       3090722.3     13904483.14
#Sta/Elev= 30
  4471.2   99.63  4541.2   99.35  4561.2   98.11  4721.2   96.82  4731.2    97.3
  4751.2   99.21  4761.2   99.43  4788.6   98.97  4836.1   99.59  4866.1   98.23
  4886.1   98.98  4906.1   98.71  4935.4   97.39  4947.5   95.97  4972.9   87.94
  4974.7   85.41  5003.9      85  5013.3      84    5024   84.57  5025.2   85.51
  5064.2   98.41  5075.4  103.04  5094.7  101.95  5104.7   100.8  5134.7   98.99
  5154.7   98.32  5224.7   97.84  5324.7   99.19  5444.7    98.4  5452.9   98.55
#Mann= 6 , 1 , 0
  4471.2      .2       0  4471.2      .1       0  4788.6     .14       0
  4947.5     .04       0  5064.2     .14       0  5452.9      .2       0
Bank Sta=4947.5,5064.2
XS Rating Curve= 0
Exp/Cntr=.3,.1

Chan Stop Cuts=-1